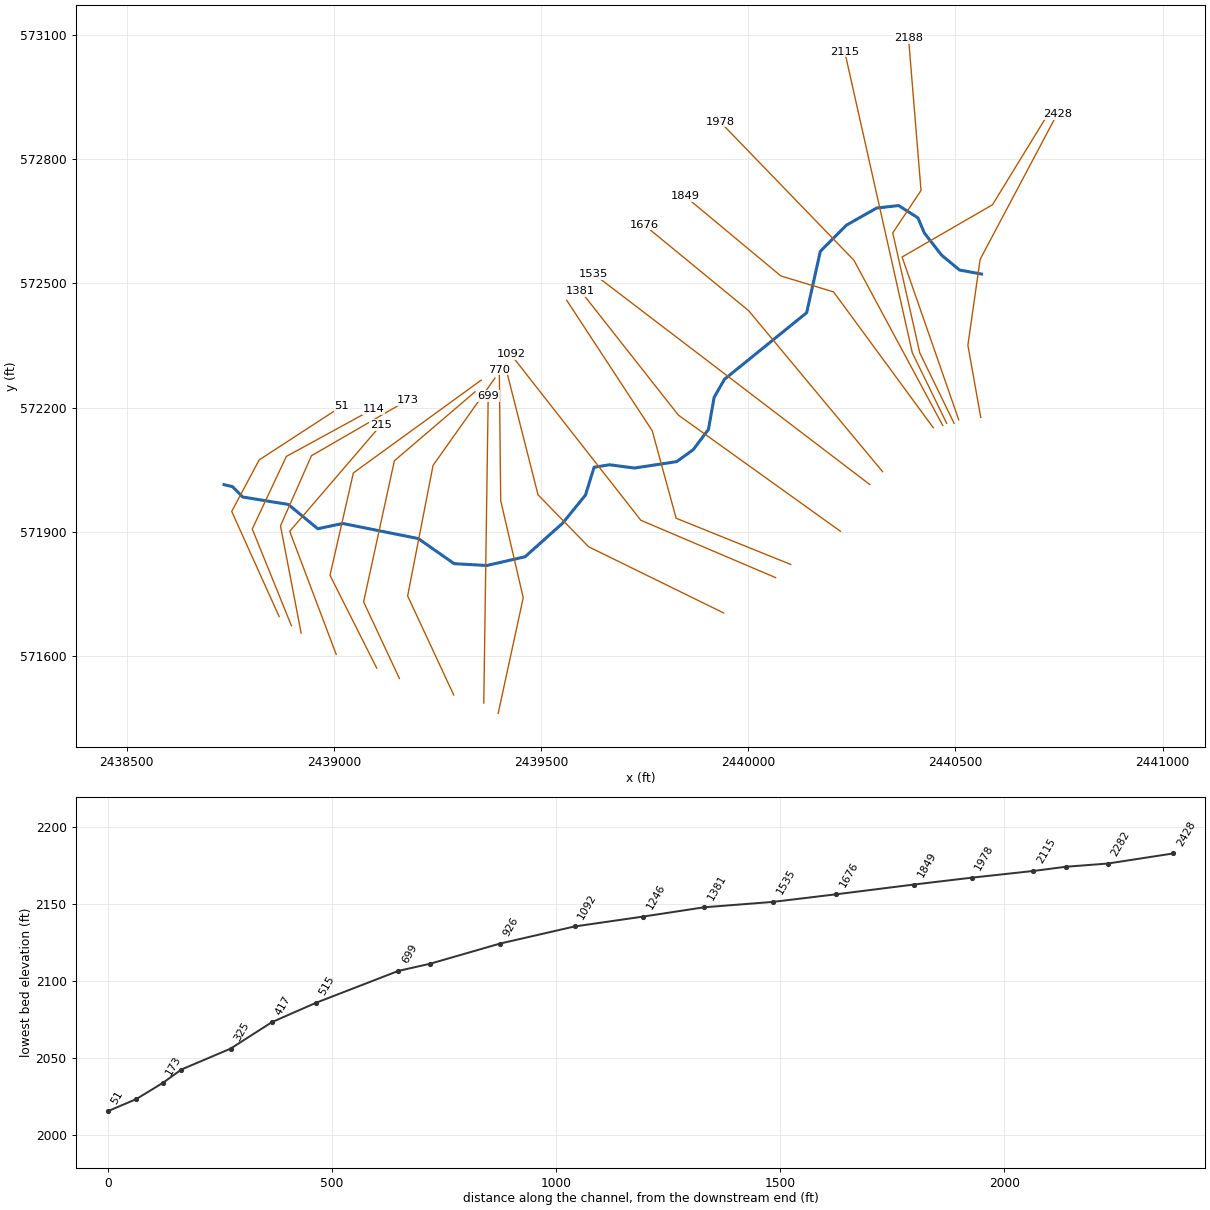
--- THORNCK_T1.prj (project) ---

Proj Title=THORNCK_T1
Current Plan=p01
Default Exp/Contr=0,0
English Units
Geom File=g01
Flow File=f01
Plan File=p01
BEGIN DESCRIPTION:
Stream Name: Thorn Creek Tributary 1
Flood Zone: Approximate
Pendlteon County, West Virginia
HEC-RAS Version: 5.0.7
Hydrology Method:
Regression
END DESCRIPTION:
DSS Export Rating Curves= 0
DSS Export Rating Curve Sorted= 0
DSS Export Volume Flow Curves= 0
DXF OffsetX= 0
DXF OffsetY= 0
DXF ScaleX= 0
DXF ScaleY= 0

--- THORNCK_T1.p01 (plan) ---

Plan Title=Floodplain
Program Version=5.07
Short Identifier=Floodplain
Geom File=g01
Flow File=f01
Subcritical Flow
K Sum by GR= 0
Std Step Tol= 0.01
Critical Tol= 0.01
Num of Std Step Trials= 20
Max Error Tol= 0.3
Flow Tol Ratio= 0.001
Split Flow NTrial= 30
Split Flow Tol= 0.02
Split Flow Ratio= 0.02
Log Output Level= 0
Friction Slope Method= 1
Unsteady Friction Slope Method= 2
Unsteady Bridges Friction Slope Method= 1
Parabolic Critical Depth
Global Vel Dist= 0 , 0 , 0
Global Log Level= 0
CheckData=True
Encroach Param=-1 ,0,0, 0
Mapping Interval=1HOUR
Computation Time Step Use Courant=        0
Computation Time Step Use Time Series=    0
Computation Time Step Count To Double=0
Computation Time Step Max Doubling=0
Computation Time Step Max Halving=0
Computation Time Step Residence Courant=0
Run HTab= 0
Run UNet= 0
Run Sediment= 0
Run PostProcess= 0
Run WQNet= 0
Run RASMapper= 0
UNET Theta= 0
UNET Theta Warmup= 0
UNET ZTol= 0
UNET ZSATol= 0
UNET MxIter= 0
UNET Max Iter WO Improvement= 0
UNET MaxInSteps= 0
UNET DtIC= 0
UNET DtMin= 0
UNET MaxCRTS= 0
UNET WFStab= 0
UNET SFStab= 0
UNET WFX= 1
UNET SFX= 1
UNET 1D Methodology=Finite Difference
UNET DSS MLevel= 1
UNET Pardiso=0
UNET DZMax Abort= 0
UNET Use Existing IB Tables= 0
UNET Froude Reduction=False
UNET Froude Limit= 0
UNET Froude Power= 0
UNET D1 Cores= 0
UNET D2 Coriolis=0
UNET D2 Cores= 0
UNET D2 Theta= 1
UNET D2 Theta Warmup= 1
UNET D2 Z Tol= 0.01
UNET D2 Volume Tol= 0.01
UNET D2 Max Iterations= 20
UNET D2 Equation= 0
UNET D2 RampUpFraction=0.1
UNET D2 TimeSlices= 1
UNET D2 BCVolumeCheck=0
UNET D1D2 MaxIter= 0
UNET D1D2 ZTol=0.01
UNET D1D2 QTol=0.1
UNET D1D2 MinQTol=1
Write IC File= 0
Write IC File at Fixed DateTime=0
Write IC File at Sim End=0
Echo Input=False
Echo Parameters=False
Echo Output=False
Write Detailed= 0
HDF Write Warmup=0
HDF Write Time Slices=0
HDF Flush=0
HDF Face Node Velocities=0
HDF Compression= 1
HDF Chunk Size= 1
HDF Spatial Parts= 1
HDF Use Max Rows=0
HDF Fixed Rows= 1
Calibration Method= 0
Calibration Iterations= 20
Calibration Max Change=0.05
Calibration Tolerance=0.2
Calibration Maximum=1.5
Calibration Minimum=0.5
Calibration Optimization Method= 1
WQ AD Non Conservative
WQ ULTIMATE=-1
WQ Max Comp Step=1HOUR
WQ Output Interval=15MIN
WQ Output Selected Increments= 0
WQ Output face flow=0
WQ Output face velocity=0
WQ Output face area=0
WQ Output face dispersion=0
WQ Output cell volume=0
WQ Output cell surface area=0
WQ Output cell continuity=0
WQ Output cumulative cell continuity=0
WQ Output face conc=0
WQ Output face dconc_dx=0
WQ Output face courant=0
WQ Output face peclet=0
WQ Output face adv mass=0
WQ Output face disp mass=0
WQ Output cell mass=0
WQ Output cell source sink temp=0
WQ Output nsm pathways=0
WQ Output nsm derived pathways=0
WQ Output MaxMinRange=-1
WQ Daily Max Min Mean=-1
WQ Daily Range=0
WQ Daily Time=0
WQ Create Restart=0
WQ Fixed Restart=0
WQ System Summary=0
WQ Write To DSS=0
WQ Use Fixed Temperature=0
Sorting and Armoring Iterations= 10
XS Update Threshold= 0.02
Bed Roughness Predictor= 0
Hydraulics Update Threshold= 0.02
Energy Slope Method= 1
Volume Change Method= 1
Sediment Retention Method= 0
XS Weighting Method= 0
Number of US Weighted Cross Sections= 1
Number of DS Weighted Cross Sections= 1
Upstream XS Weight=0
Main XS Weight=1
Downstream XS Weight=0
Number of DS XS's Weighted with US Boundary= 1
Upstream Boundary Weight= 1
Weight of XSs Associated with US Boundary= 0
Number of US XS's Weighted with DS Boundary= 1
Downstream Boundary Weight= 0.5
Weight of XSs Associated with DS Boundary= 0.5
Percentile Method= 0
Sediment Output Level= 3
Mass or Volume Output= 0
Output Increment Type= 1
Profile and TS Output Increment= 1
XS Output Flag= 0
XS Output Increment= 10
Write Gradation File= 0
Read Gradation Hotstart= 0
Write HDF5 File= 1
Write Binary Output= 1
Write DSS Sediment File= 0
SV Curve= 0
Specific Gage Flag= 0

--- THORNCK_T1.f01 (steady flow) ---

Flow Title=Flows
Program Version=5.07
Number of Profiles= 6
Profile Names=P100yr,P10yr,P25yr,P50yr,P500yr,P101yr
River Rch & RM=THORNCK_T1,Main            ,2428
     407     191     270     336     594     495
River Rch & RM=THORNCK_T1,Main            ,1978
     646     302     427     533     949     787
Boundary for River Rch & Prof#=THORNCK_T1,Main            , 1
Up Type= 0
Dn Type= 3
Dn Slope=0.14849
Boundary for River Rch & Prof#=THORNCK_T1,Main            , 2
Up Type= 0
Dn Type= 3
Dn Slope=0.14849
Boundary for River Rch & Prof#=THORNCK_T1,Main            , 3
Up Type= 0
Dn Type= 3
Dn Slope=0.14849
Boundary for River Rch & Prof#=THORNCK_T1,Main            , 4
Up Type= 0
Dn Type= 3
Dn Slope=0.14849
Boundary for River Rch & Prof#=THORNCK_T1,Main            , 5
Up Type= 0
Dn Type= 3
Dn Slope=0.14849
Boundary for River Rch & Prof#=THORNCK_T1,Main            , 6
Up Type= 0
Dn Type= 3
Dn Slope=0.14849
DSS Import GetInterval= 0
DSS Import GetPeak= 0
DSS Import FillOption= 0

--- THORNCK_T1.g01 (geometry) ---

Geom Title=Geometry
Program Version=5.07

River Reach=THORNCK_T1      ,Main
Reach XY= 30
2440562.92100003 572522.554000022440509.98800001 572532.25500001
2440466.74599999572568.1720000062440425.21900001572621.439999998
2440409.59999999572658.2469999942440363.09000003572687.850999996
2440309.97999999572681.7629999972440237.21399999572640.546000019
2440174.21000001572577.4640000022440141.10000002572429.146000013
2439942.80399999572268.581000015     2439917.794572224.732000008
2439904.11300004572147.3540000022439867.21100003572098.535999998
2439827.43400002572069.8030000032439725.36300004572054.392000005
2439665.57499999572062.2569999992439628.18800002572056.356999993
2439607.43000001571989.1640000052439552.14500001571921.226999998
2439461.71500003571840.3110000192439369.20500004571819.208000019
2439290.40200001571823.6389999992439203.86500001571884.183000013
2439021.84900001571920.5790000112438961.33700004571907.937999994
2438890.14900002571966.5729999992438780.09800002571984.435000002
2438755.68500003572009.5040000082438735.13052902572014.310290188

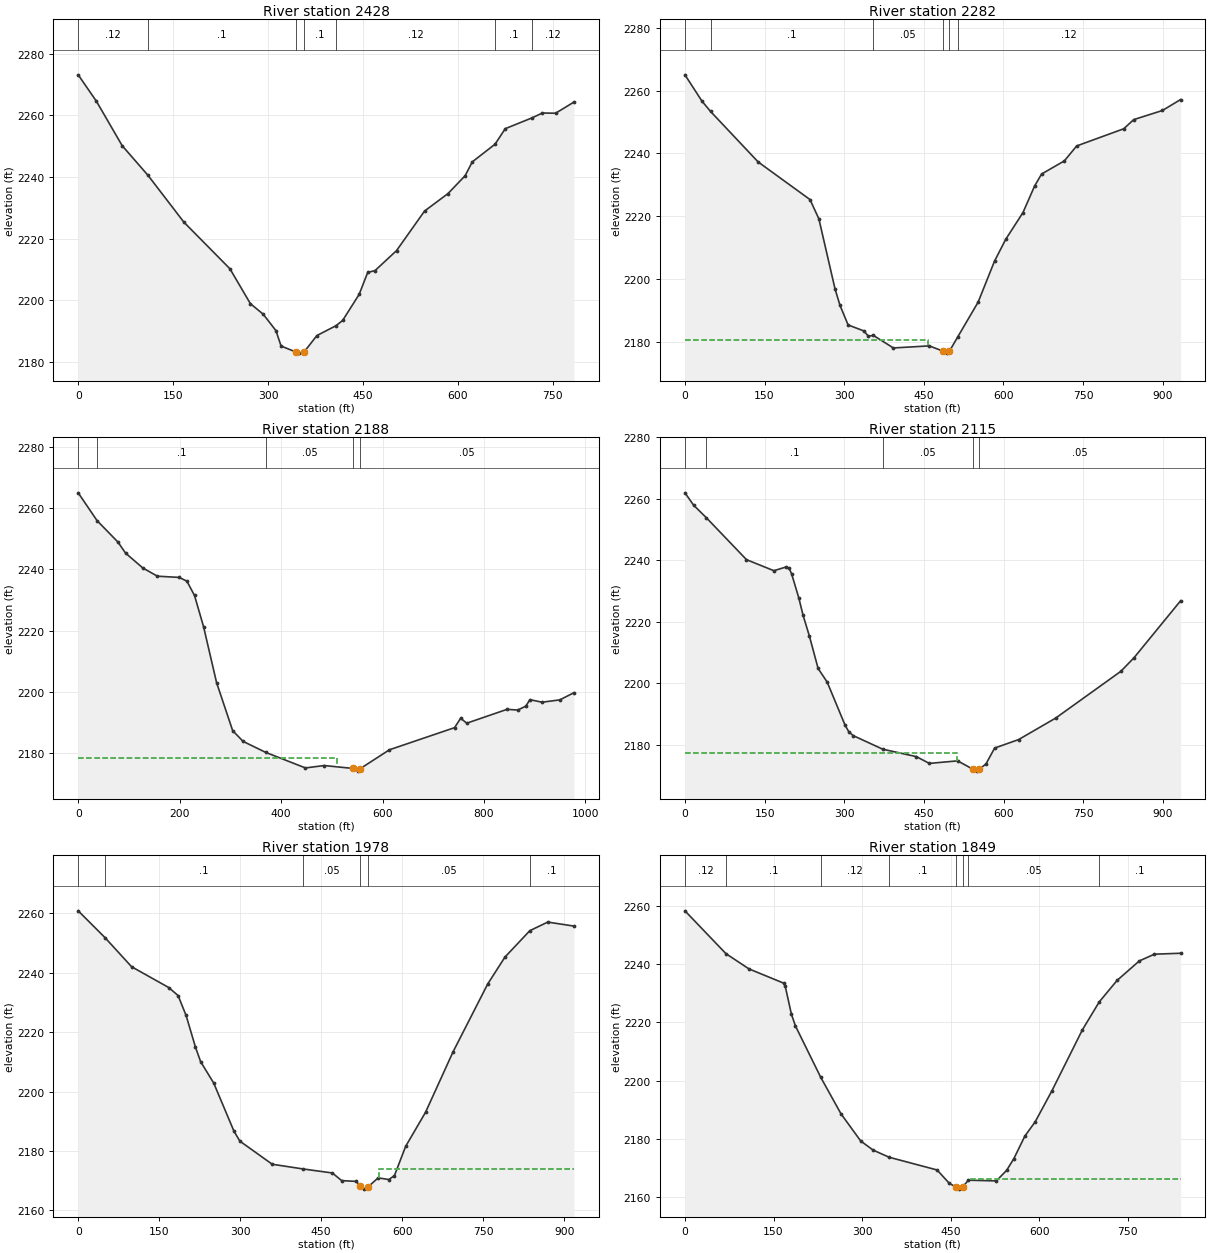
Type RM Length L Ch R = 1 ,2428    ,146.1,146.1,146.1
XS GIS Cut Line= 4
 2440561.2918726572176.5620028462440530.24139949572350.817715287
2440559.82959353572558.079967657     2440745.749      572908.792
#Sta/Elev= 30
       0 2273.12    28.9 2264.52    69.5 2250.15  110.192240.567     167 2225.37
   239.8 2210.24   272.1 2198.95   292.4 2195.52   312.5  2190.2   320.6 2185.21
   344.8 2183.21   348.8 2182.91     357  2183.3   377.2  2188.6  407.572191.825
   417.9 2193.51     444 2201.96   457.5 2209.06   469.1 2209.67     503 2216.13
   547.3 2228.96   584.3 2234.62   611.4 2240.41   622.8 2244.91  658.782250.647
   674.8 2255.66   717.22259.175   733.7 2260.75   754.4 2260.67   783.3 2264.28
#Mann= 7 ,-1 , 0
       0     .12       0  110.19      .1       0   344.8    .045       0
     357      .1       0  407.57     .12       0  658.78      .1       0
   717.2     .12       0
Bank Sta=344.8,357
XS Rating Curve= 0 ,0
Exp/Cntr=0.3,0.1

Type RM Length L Ch R = 1 ,2282    ,87.2,94.2,98.1
XS GIS Cut Line= 4
2440508.20352384572170.6836540922440371.44687989572563.600258816
2440589.54364559572689.6465535942440728.47408826572916.304260498
#Sta/Elev= 30
       0 2265.07    32.1 2256.67   48.232253.401     138 2237.28   235.6  2225.3
   252.3 2219.16   282.7 2196.83   292.1 2191.57   307.4 2185.33     337 2183.43
   345.6 2181.74  354.832182.017   392.6    2178   460.3 2178.66   485.82177.009
   493.6 2176.35   498.3 2176.97  513.672181.461   552.3  2192.6   583.3 2205.72
   604.5 2212.69   636.8 2221.16   658.6 2229.58   671.8 2233.44   714.7 2237.63
     738  2242.4   826.6 2247.87   845.4 2250.79   899.5  2253.7   933.8  2257.2
#Mann= 6 ,-1 , 0
       0     .12       0   48.23      .1       0  354.83     .05       0
   485.8    .045       0   498.3     .05       0  513.67     .12       0
#XS Ineff= 2 , 0
           458.2 2180.67
Permanent Ineff=
       F       F
Bank Sta=485.8,498.3
XS Rating Curve= 0 ,0
Exp/Cntr=0.3,0.1

Type RM Length L Ch R = 1 ,2188    ,60.8,72.1,79.5
XS GIS Cut Line= 5
2440496.90803516572162.4182185052440413.95768661572332.683366533
2440348.92674629572621.8196561642440417.14163794572724.141993636
2440387.03608356573091.342827757
#Sta/Elev= 30
       0 2264.92   37.212255.856    78.4 2248.87    93.4 2245.27   127.5 2240.42
   156.2 2237.75   199.2 2237.35   214.3 2236.13   229.3 2231.46   247.1 2221.32
   272.8 2203.07   304.5 2187.43     325 2183.92  369.562180.337     448 2175.26
   484.9 2176.04   542.4 2175.09     552 2174.22  555.55 2174.98   613.6 2181.18
     742 2188.39     754 2191.46     766 2189.84   845.5 2194.36   866.4 2194.12
   882.4 2195.39   890.5 2197.51   914.5 2196.68   949.4 2197.44   977.2 2199.77
#Mann= 5 ,-1 , 0
       0     .12       0   37.21      .1       0  369.56     .05       0
   542.4    .045       0  555.55     .05       0
#XS Ineff= 2 , 0
          509.93 2178.55
Permanent Ineff=
       F       F
Bank Sta=542.4,555.55
XS Rating Curve= 0 ,0
Exp/Cntr=0.3,0.1

Type RM Length L Ch R = 1 ,2115    ,130.7,137.5,143.4
XS GIS Cut Line= 3
2440478.99756726572162.4182185052440396.04721871572332.683366533
     2440233.118      573058.701
#Sta/Elev= 30
       0 2261.96    16.2 2257.97   40.562253.821   115.9 2240.24   167.5 2236.65
   189.7 2237.82     196 2237.51   200.9 2235.61   214.3 2227.87   222.5 2222.15
   234.4 2215.38   250.8 2204.87   267.9 2200.44   301.3 2186.55   308.6 2184.29
   316.8 2183.06  372.492178.636   435.7 2176.23   460.3 2174.02   513.5 2174.85
   542.1 2172.15   550.4 2171.51   554.5 2172.18   566.8 2173.82   583.2    2179
   628.3 2181.76     698 2188.73     821 2203.96   845.6 2208.34   933.5 2226.89
#Mann= 5 ,-1 , 0
       0     .12       0   40.56      .1       0  372.49     .05       0
   542.1    .045       0   554.5     .05       0
#XS Ineff= 2 , 0
           512.5 2177.53
Permanent Ineff=
       F       F
Bank Sta=542.1,554.5
XS Rating Curve= 0 ,0
Exp/Cntr(USF)=0,0
Exp/Cntr=0.3,0.1

Type RM Length L Ch R = 1 ,1978    ,122.7,128.7,134.9
XS GIS Cut Line= 3
2440469.42007379572157.2686643132440255.37327063  572555.5569842
     2439931.791       572890.47
#Sta/Elev= 30
       0 2260.88   49.972251.791    98.9 2242.05   167.7 2235.04     185 2232.34
   199.8 2225.64   217.2 2214.94   226.7 2210.09     251 2202.85   288.4 2186.68
   299.4 2183.31   359.3 2175.53  416.732173.935   470.7 2172.59   487.8 2170.02
   515.3 2169.75   521.82168.079   530.1 2167.15   536.42167.867   555.5 2170.94
   575.3 2170.38   585.6 2171.71   606.4 2181.56   643.2 2193.03   694.1 2213.37
   758.3 2236.23   790.3 2245.31  836.272254.186   869.5 2257.09   917.9 2255.74
#Mann= 6 ,-1 , 0
       0     .12       0   49.97      .1       0  416.73     .05       0
   521.8    .045       0   536.4     .05       0  836.27      .1       0
#XS Ineff= 2 , 0
                          557.94         2173.99
Permanent Ineff=
       F       F
Bank Sta=521.8,536.4
XS Rating Curve= 0 ,0
Exp/Cntr(USF)=0,0
Exp/Cntr=0.3,0.1

Type RM Length L Ch R = 1 ,1849    ,179.5,173.3,167.3
XS GIS Cut Line= 4
2440446.77681896572151.6255061342440206.08752547572479.447783829
2440078.98626509572517.8471568782439848.48009312572709.683683643
#Sta/Elev= 30
       0 2258.36   69.322243.661   108.4  2238.4   167.1 2233.51   169.9 2232.37
   180.3 2222.82   187.1  2218.8  229.932201.145   264.3 2188.58   297.7 2179.24
   318.7 2176.12  345.732173.672     427 2169.29   447.9 2164.65   458.62163.498
   464.6 2162.71   470.32163.448   479.92165.778   527.3 2165.53   544.8 2169.18
   556.9 2173.16   575.6 2180.93   593.1 2185.85   621.5 2196.53     673 2217.45
  701.582227.063   731.9 2234.47   769.4 2241.13   794.9 2243.46   839.4 2243.78
#Mann= 8 ,-1 , 0
       0     .12       0   69.32      .1       0  229.93     .12       0
  345.73      .1       0   458.6    .045       0   470.3      .1       0
   479.9     .05       0  701.58      .1       0
#XS Ineff= 2 , 0
                             485         2166.36
Permanent Ineff=
       F       F
Bank Sta=458.6,470.3
XS Rating Curve= 0 ,0
Exp/Cntr=0.3,0.1

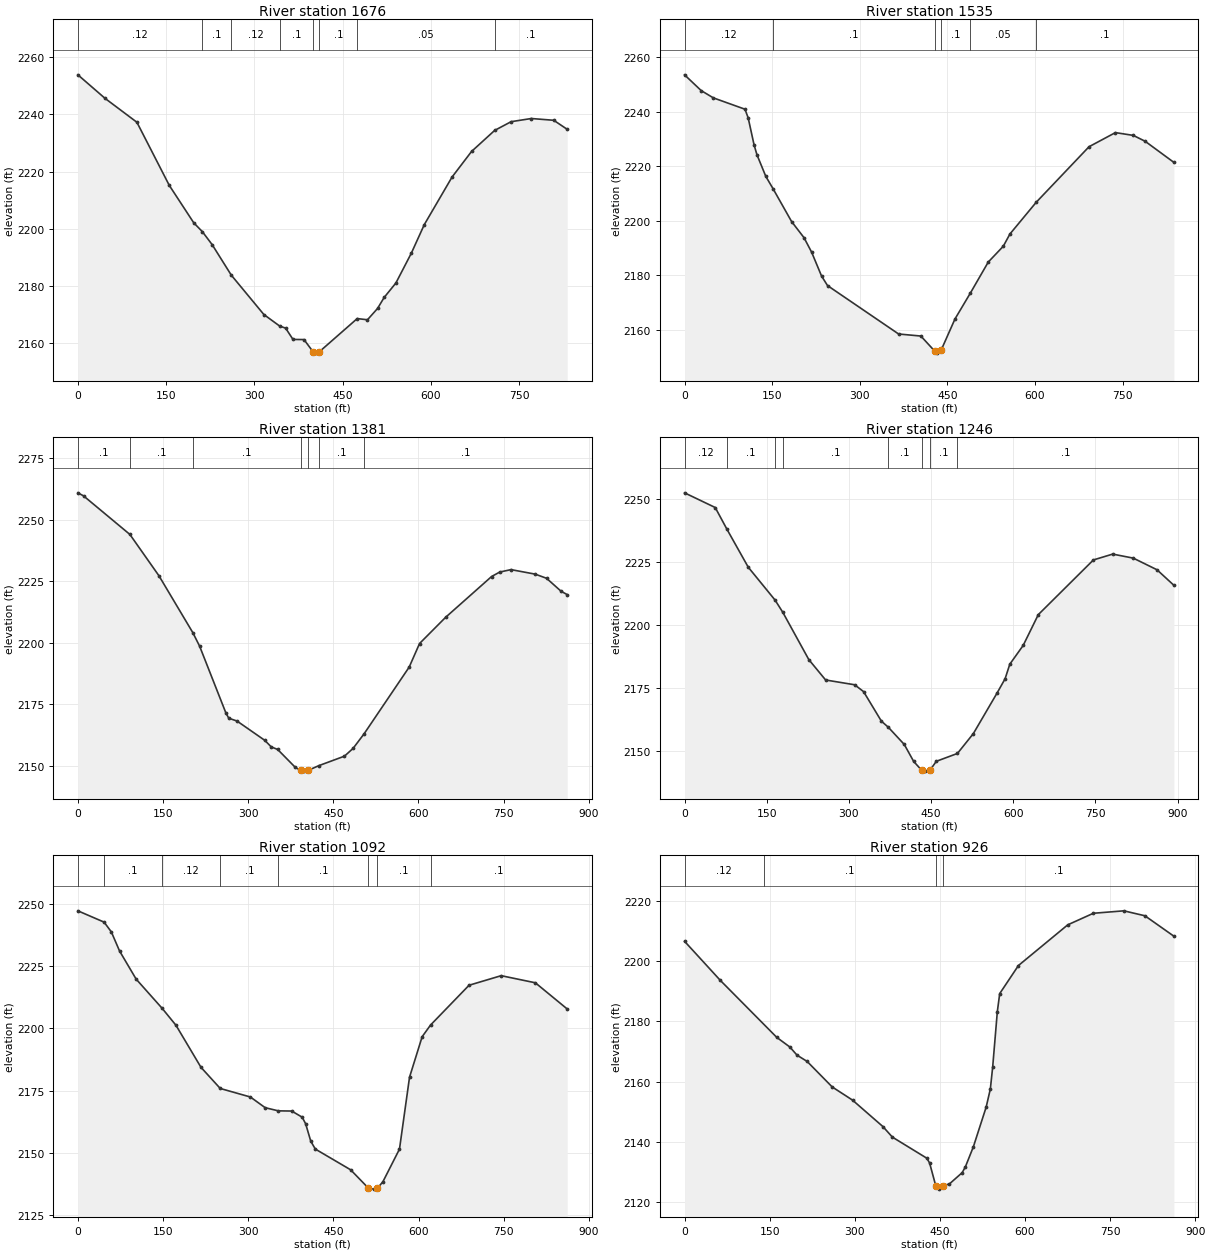
Type RM Length L Ch R = 1 ,1676    ,139.5,140.9,144
XS GIS Cut Line= 3
     2440324.464      572045.6042440001.29169071572434.002622119
     2439748.991      572641.102
#Sta/Elev= 30
       0  2253.9    46.3 2245.63   100.3 2237.28   155.3 2215.17   196.9 2202.05
  211.482198.955   228.2  2194.4  260.742183.698   316.1  2169.9  343.132165.834
   353.1 2165.13   365.6 2161.17   384.3 2161.12   399.72156.854   405.1 2156.37
   410.3 2156.83  474.782168.478   492.2 2168.06   509.3 2172.01   520.6 2175.89
   540.5 2180.94   566.7 2191.37   588.8 2201.41     636 2218.09   669.1 2227.04
  708.432234.428   736.4 2237.48   770.7 2238.59   808.8 2237.97   831.7  2234.8
#Mann= 8 ,-1 , 0
       0     .12       0  211.48      .1       0  260.74     .12       0
  343.13      .1       0   399.7    .045       0   410.3      .1       0
  474.78     .05       0  708.43      .1       0
Bank Sta=399.7,410.3
XS Rating Curve= 0 ,0
Exp/Cntr=0.3,0.1

Type RM Length L Ch R = 1 ,1535    ,155.8,154.3,155.3
XS GIS Cut Line= 2
     2440293.243      572014.712     2439627.123      572522.808
#Sta/Elev= 30
       0 2253.58    28.5 2247.79    49.2 2245.13   103.4 2240.96   108.9 2237.81
     119 2227.89     124 2224.22   139.1 2216.31  151.572211.754   183.3 2199.71
   204.5 2193.81   217.6 2188.47   234.6 2179.71   244.8 2176.22   366.5 2158.45
   404.6  2157.7   428.7 2152.07   432.5 2151.43   439.1 2152.41     463 2163.97
  489.412173.494     520 2184.86   545.7 2190.66   557.1 2195.16  602.022206.785
   692.5 2227.19   737.7 2232.37   768.3 2231.35   788.6 2229.19   837.8 2221.44
#Mann= 6 ,-1 , 0
       0     .12       0  151.57      .1       0   428.7    .045       0
   439.1      .1       0  489.41     .05       0  602.02      .1       0
Bank Sta=428.7,439.1
XS Rating Curve= 0 ,0
Exp/Cntr=0.3,0.1

Type RM Length L Ch R = 1 ,1381    ,143,135.2,126.8
XS GIS Cut Line= 3
     2440222.644      571901.7752439831.61269071572182.090251301
     2439595.949      572481.278
#Sta/Elev= 30
       0 2260.98     9.9 2259.75   91.632244.067   142.8 2227.28  202.542204.146
   214.5 2198.65   260.8  2171.5   265.8 2169.41   280.4 2168.25   329.1 2160.44
   340.6 2157.77     352  2156.7   383.2 2149.39   392.2 2148.24   398.6 2147.91
   405.72148.214  424.342150.125   469.6 2153.99   484.8 2157.15  504.192163.074
   583.6 2190.17   601.9 2199.76   647.8  2210.4   728.8 2226.98   743.1 2228.79
     763 2229.78   805.7 2227.94   825.6 2226.26   851.4 2220.95     862 2219.63
#Mann= 7 ,-1 , 0
       0      .1       0   91.63      .1       0  202.54      .1       0
   392.2    .045       0   405.7      .1       0  424.34      .1       0
  504.19      .1       0
Bank Sta=392.2,405.7
XS Rating Curve= 0 ,0
Exp/Cntr=0.3,0.1

Type RM Length L Ch R = 1 ,1246    ,148.4,153.8,158.3
XS GIS Cut Line= 4
2440102.54175037571821.7974797412439826.14871207571933.259827746
 2439768.5685279572144.191318714     2439562.188      572459.126
#Sta/Elev= 30
       0 2252.51      56 2246.67   77.532237.974   116.3 2222.94  165.312209.857
  179.362205.017   226.8 2186.24   257.5 2178.13   310.5 2176.23   326.8  2173.5
   359.3 2161.77  371.832159.368   401.1  2152.5   418.2 2145.77   433.22142.167
   438.8 2141.91     448 2142.26   459.5 2145.81   498.12148.934   527.2 2156.84
   570.3 2172.89   585.1 2178.62   593.7 2184.41   618.1 2191.86   645.7  2204.1
   746.3 2225.84   781.5 2228.16   819.1 2226.56   862.4 2221.93   893.2 2215.76
#Mann= 8 ,-1 , 0
       0     .12       0   77.53      .1       0  165.31      .1       0
  179.36      .1       0  371.83      .1       0   433.2    .045       0
     448      .1       0   498.1      .1       0
Bank Sta=433.2,448
XS Rating Curve= 0 ,0
Exp/Cntr=0.3,0.1

Type RM Length L Ch R = 1 ,1092    ,165.1,166.3,166.1
XS GIS Cut Line= 3
2440066.19500521571789.9794024172439740.95354162571928.363553583
 2439427.4344817572328.530603182
#Sta/Elev= 30
       0 2247.25   46.182242.708    58.9 2238.79    73.4 2231.11   102.6 2219.82
  148.462208.064   172.8 2201.26   216.8 2184.38  250.752175.883   303.8 2172.46
   329.9 2168.16  353.042166.896   376.6 2166.82     395 2164.35   401.1 2161.72
   410.2 2154.68   418.2 2151.54   480.4 2143.21   511.8 2135.82     522 2135.45
   527.32135.744   537.2 2138.42   566.4 2151.53   584.1 2180.42   606.3 2196.67
  621.062201.353   688.9 2217.35   745.5  2221.2   805.7 2218.34   861.8 2207.82
#Mann= 8 ,-1 , 0
       0     .12       0   46.18      .1       0  148.46     .12       0
  250.75      .1       0  353.04      .1       0   511.8    .045       0
   527.3      .1       0  621.06      .1       0
Bank Sta=511.8,527.3
XS Rating Curve= 0 ,0
Exp/Cntr=0.3,0.1

Type RM Length L Ch R = 1 ,926     ,159.6,155.8,148.7
XS GIS Cut Line= 4
2439940.76515345571704.7189601412439614.96384768571864.372735343
2439492.93646634571989.7075945892439412.95817865572304.480964271
#Sta/Elev= 30
       0 2206.57    62.9 2193.63   162.6 2174.68   185.5 2171.51   198.2  2168.8
   216.1  2166.7   260.2 2158.25   296.1 2153.87   349.7 2145.08   366.3  2141.6
     427  2134.6   431.9 2133.03   442.7 2125.51   449.1 2124.34   454.9 2125.52
   466.6 2126.02   489.3  2129.8   494.9  2131.7     509 2138.35   531.6 2151.54
     539 2157.58   543.1 2164.84   551.3 2183.24   555.5 2189.22   588.5 2198.53
   675.4 2212.03   720.6 2215.87   774.3 2216.68   811.4 2215.04   862.5 2208.26
#Mann= 4 ,-1 , 0
       0     .12       0  139.32      .1       0   442.7    .045       0
   454.9      .1       0
Bank Sta=442.7,454.9
XS Rating Curve= 0 ,0
Exp/Cntr=0.3,0.1

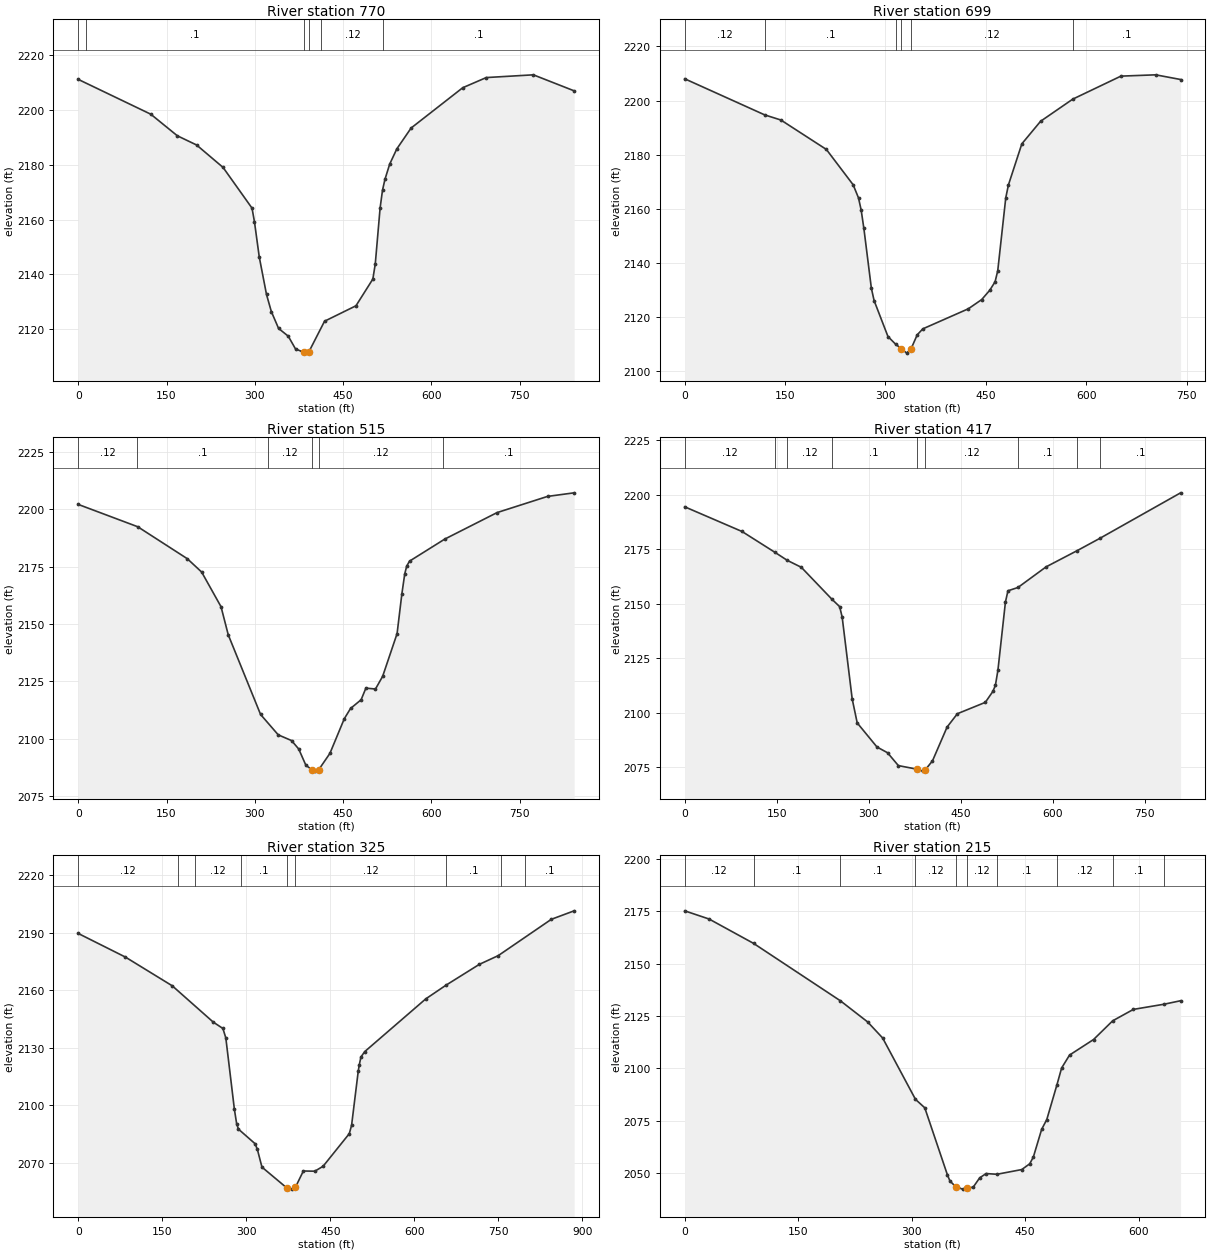
Type RM Length L Ch R = 1 ,770     ,72.8,70.9,68.1
XS GIS Cut Line= 4
2439396.73442007571462.3397920282439457.19501352 571741.42185079
2439402.81186762571975.6366765812439399.44533623572292.171451673
#Sta/Elev= 30
       0 2211.23   123.3 2198.51   168.4 2190.63   201.1 2187.27   246.1 2179.07
   295.3  2164.2   299.4 2159.28   307.6 2146.36   319.9 2132.67   328.1 2126.44
   340.4 2120.28   356.9 2117.43   369.2 2112.78   383.32111.546   389.7 2111.25
   391.9 2111.72   418.5  2122.9   471.9 2128.54   500.6 2138.31   504.7 2143.81
   512.9 2164.22     517 2170.76   521.1 2174.68   529.2 2180.28   541.3 2185.84
   565.6 2193.46   653.3 2208.18   693.3 2211.89   773.3 2212.89   842.6 2207.04
#Mann= 6 ,-1 , 0
       0     .12       0   13.48      .1       0   383.3    .045       0
   391.9      .1       0  413.29     .12       0  518.41      .1       0
Bank Sta=383.3,391.9
XS Rating Curve= 0 ,0
Exp/Cntr=0.3,0.1

Type RM Length L Ch R = 1 ,699     ,184.9,184.2,181.7
XS GIS Cut Line= 2
2439361.99075979571487.2461437782439372.67859833572228.113917463
#Sta/Elev= 30
       0 2208.06   119.7 2194.69   143.7 2192.81   211.7 2181.92   251.7 2168.85
   259.7 2163.98   263.7 2159.45   267.7 2152.71   278.9 2130.59     283 2126.01
   303.7 2112.73   315.5  2109.8   323.7 2108.27   331.7 2106.59   338.42108.292
   347.4 2113.36   355.7 2115.56   423.7 2122.98   443.7 2126.39   455.7 2129.83
   463.7 2132.96   467.7 2137.06   479.7 2164.07   483.7 2168.83   503.7    2184
   531.7 2192.34   579.7 2200.52   651.7 2209.04   703.7 2209.52   740.9 2207.79
#Mann= 6 ,-1 , 0
       0     .12       0   119.7      .1       0   315.5     .12       0
   323.7    .045       0   338.4     .12       0   579.7      .1       0
Bank Sta=323.7,338.4
XS Rating Curve= 0 ,0
Exp/Cntr(USF)=0,0
Exp/Cntr=0.3,0.1

Type RM Length L Ch R = 1 ,515     ,98.2,98,97.8
XS GIS Cut Line= 4
2439289.37558762571506.9152852152439178.26435154571745.721523951
2439239.62428789572060.813088951 2439388.8781871572271.426924504
#Sta/Elev= 30
       0 2202.06   101.1 2192.33   185.3  2178.4   209.7 2172.58   242.6 2157.48
   254.9 2145.21   309.8 2110.52   339.8 2101.63   362.4 2099.14   374.6 2095.46
   386.8 2088.36   397.22086.421   403.1 2085.82   408.72086.485   427.6 2093.56
     452 2108.65   462.6 2113.12   480.6 2116.93   488.7 2121.99     505 2121.61
   517.2 2127.15   541.7 2145.76   549.8 2163.03   554.7 2171.77     558 2175.14
   562.8 2177.33   622.6 2186.93   711.5 2198.49   797.3 2205.55   842.5 2207.11
#Mann= 6 ,-1 , 0
       0     .12       0  100.36      .1       0  322.99     .12       0
   397.2    .045       0   408.7     .12       0  619.44      .1       0
Bank Sta=397.2,408.7
XS Rating Curve= 0 ,0
Exp/Cntr(USF)=0,0
Exp/Cntr=0.3,0.1

Type RM Length L Ch R = 1 ,417     ,92.2,92.1,91.8
XS GIS Cut Line= 4
2439158.33076442571546.6236394662439071.99237694571731.403926684
2439146.22725216572071.9160716882439340.69034919572238.137640102
#Sta/Elev= 30
       0 2194.42    93.5  2183.1   147.3 2173.52   167.2 2169.88   190.1  2166.7
   239.4 2152.23   252.6 2148.66   256.7 2143.85     273 2106.42   281.2 2095.39
   313.4 2084.36   330.6 2081.73   348.3 2075.83   378.1 2074.22   387.7  2073.3
   391.72073.758   403.9 2078.01   427.7  2093.5   444.5 2099.61     490 2104.81
   502.3 2109.82   506.4 2112.58   510.5 2119.46   522.8 2150.82   526.9 2155.93
   543.2 2157.45     589 2166.89   640.1 2174.39   676.9    2180   808.3 2200.82
#Mann= 9 ,-1 , 0
       0     .12       0   147.3      .1       0   167.2     .12       0
   239.4      .1       0   378.1    .045       0   391.7     .12       0
   543.2      .1       0   640.1     .12       0   676.9      .1       0
Bank Sta=378.1,391.7
XS Rating Curve= 0 ,0
Exp/Cntr(USF)=0,0
Exp/Cntr=0.3,0.1

Type RM Length L Ch R = 1 ,325     ,114.3,109.7,101.9
XS GIS Cut Line= 4
2439103.63740194571571.591974873 2438990.8677892571795.472823688
2439047.25259557572042.5709457142439355.71065394 572266.45179453
#Sta/Elev= 30
       0 2189.61    84.3 2177.26   167.9 2162.26   241.1  2143.3   258.3 2139.99
   263.5 2135.03   278.8 2097.77   282.9  2090.1   286.1 2087.41   315.7 2079.82
   319.8 2076.86     328 2067.59   372.12056.785   381.4  2056.1   387.72057.043
   401.9 2065.57   422.4 2065.46   437.2 2068.06   483.9 2085.06     488 2089.43
   499.9 2117.73   501.8 2121.08   504.7  2125.1   511.5 2127.92   620.4 2155.44
   656.7 2162.62     716 2173.46   749.8 2178.03   844.5 2196.98   885.3 2201.42
#Mann= 9 ,-1 , 0
       0     .12       0  178.92      .1       0  209.23     .12       0
  289.93      .1       0   372.1    .045       0   387.7     .12       0
   656.7      .1       0  754.53     .12       0  797.61      .1       0
Bank Sta=372.1,387.7
XS Rating Curve= 0 ,0
Exp/Cntr(USF)=0,0
Exp/Cntr=0.3,0.1

Type RM Length L Ch R = 1 ,215     ,38.7,41.5,45.9
XS GIS Cut Line= 3
2439005.82650991 571604.720498332438893.66729627571901.659999186
2439113.95121946572158.254459165
#Sta/Elev= 30
       0 2175.09    32.3 2171.18      91  2159.6   205.8 2132.25   241.8 2122.19
   261.7 2114.52   305.1  2085.3   317.4 2081.27   347.4 2049.25   350.7 2046.39
   358.5 2043.63   367.3 2042.54   373.82042.943   381.5 2043.53     390 2047.93
   398.5 2049.96   412.7 2049.61   445.6 2051.86   456.1  2054.6   460.9  2057.8
   471.9 2071.02   478.7  2075.7   492.1 2092.22   498.3 2100.24   508.8  2106.4
   540.5 2113.79   565.8 2122.71   593.2 2128.15   633.9 2130.62   655.6 2132.27
#Mann= 10 ,-1 , 0
       0     .12       0      91      .1       0   205.8      .1       0
   305.1     .12       0   358.5    .045       0   373.8     .12       0
   412.7      .1       0   492.1     .12       0   565.8      .1       0
   633.9     .12       0
Bank Sta=358.5,373.8
XS Rating Curve= 0 ,0
Exp/Cntr(USF)=0,0
Exp/Cntr=0.3,0.1

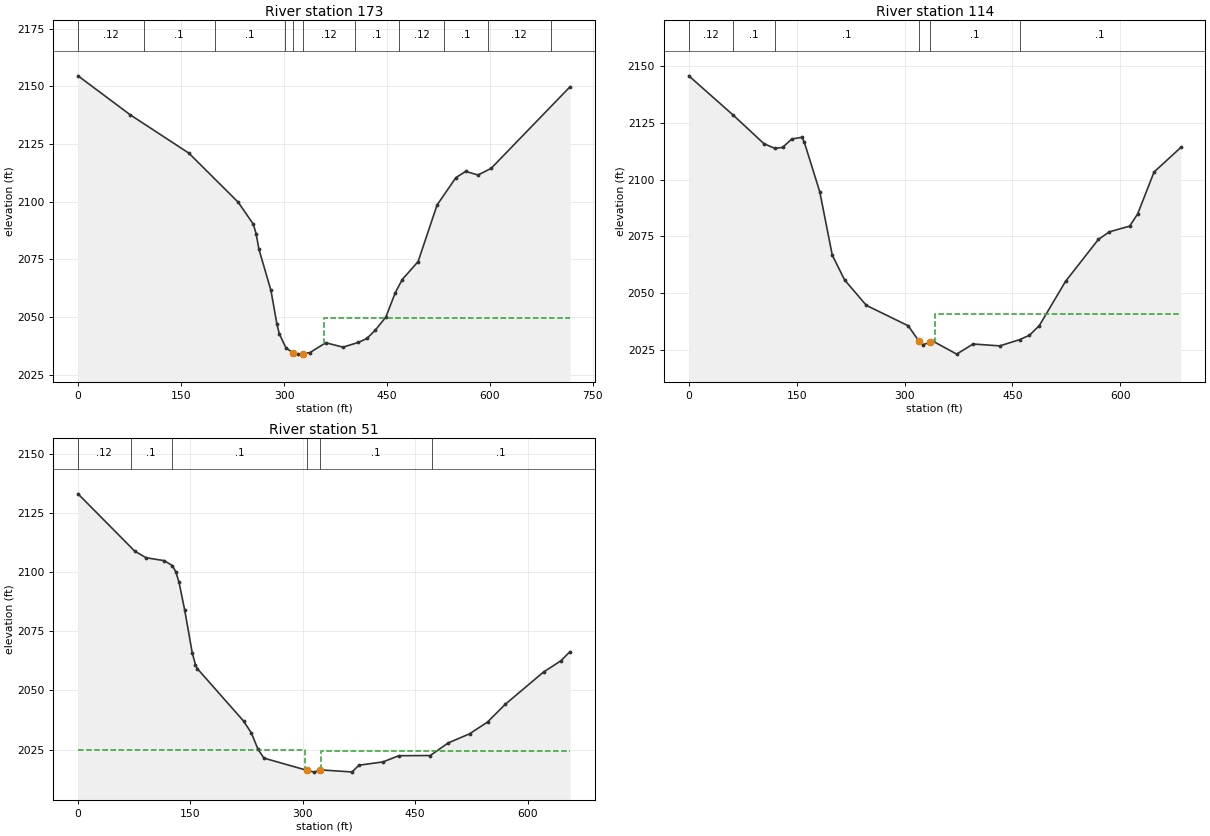
Type RM Length L Ch R = 1 ,173     ,61.4,59.3,59.9
XS GIS Cut Line= 4
2438921.21596957571656.1691844252438871.46466983571914.875943056
2438946.09161944572084.0303621622439178.26435154572218.358871451
#Sta/Elev= 30
       0 2154.57    76.1 2137.65   161.6    2121   233.3 2099.74   255.3 2090.23
   259.4 2086.06   263.4 2079.43     281 2061.47   289.7 2046.83   293.2 2042.65
   302.8 2036.58   313.12034.398   320.3 2033.84   328.32034.067   337.8 2034.51
   360.8 2038.77   385.9 2036.87   408.5 2038.94   420.7 2040.62   432.8 2044.18
   448.3 2049.87     462 2060.41   472.2 2066.19   495.3 2073.98     523 2098.56
   550.4 2110.41   564.6  2113.1   582.6 2111.56   601.6  2114.4   716.6 2149.82
#Mann= 11 ,-1 , 0
       0     .12       0   95.58      .1       0  199.18      .1       0
  301.78     .12       0   313.1    .045       0   328.3     .12       0
  402.73      .1       0  468.22     .12       0  533.53      .1       0
   596.5     .12       0   688.9      .1       0
#XS Ineff= 2 , 0
                          358.28         2049.37
Permanent Ineff=
       F       F
Bank Sta=313.1,328.3
XS Rating Curve= 0 ,0
Exp/Cntr(USF)=0,0
Exp/Cntr=0.3,0.1

Type RM Length L Ch R = 1 ,114     ,63.5,63.5,63.5
XS GIS Cut Line= 4
2438897.70180036571674.113968639 2438803.2944047571907.308304909
2438885.59828809572082.4057823162439095.39250065572196.985698408
#Sta/Elev= 30
       0 2145.59    61.2 2128.48   104.4  2115.8   119.6 2113.72   130.3 2114.14
   143.2 2117.83   157.1 2118.57   160.5 2116.53   182.1 2094.63   199.5 2066.77
   216.6 2055.92   246.8 2044.76     305 2035.77     320 2029.03   326.3 2027.46
   335.2 2028.61   339.5 2028.99   372.5 2023.31   395.2 2027.76   432.3 2026.93
     460 2029.67   473.7 2031.62   487.4 2035.87   523.8 2055.27   569.4 2073.68
   584.8 2077.05     613 2079.56   624.1 2084.92   646.9 2103.33   684.1 2114.12
#Mann= 6 ,-1 , 0
       0     .12       0    61.2      .1       0   119.6      .1       0
     320    .045       0   335.2      .1       0     460      .1       0
#XS Ineff= 2 , 0
                          342.94          2041.1
Permanent Ineff=
       F       F
Bank Sta=320,335.2
XS Rating Curve= 0 ,0
Exp/Cntr(USF)=0,0
Exp/Cntr=0.3,0.1

Type RM Length L Ch R = 1 ,51      ,,,
XS GIS Cut Line= 4
2438868.14791652571695.9702242152438753.71992712571949.701852872
2438820.05499344572074.0801022142439019.06019239 572203.43348153
#Sta/Elev= 30
       0 2133.13    75.8 2108.87      91  2106.1   115.2 2104.86   126.1 2102.74
   130.5 2100.13   134.8 2095.76   142.4 2083.93   152.4    2066   156.8  2060.8
   159.1 2059.25     221 2037.03   231.4 2031.97   240.2 2025.14   248.2 2021.36
   306.12016.152   315.5 2015.44   322.72016.408   365.8 2015.51   374.9 2018.36
   407.1 2019.76   428.1 2022.38   470.2 2022.46   494.1 2027.79   522.7 2031.66
   546.6 2036.63   570.4 2044.17   621.3 2057.75   644.5 2062.52   656.7 2066.41
#Mann= 6 ,-1 , 0
       0     .12       0   70.18      .1       0  125.23      .1       0
   306.1    .045       0   322.7      .1       0  471.84      .1       0
#XS Ineff= 2 , 0
          302.81 2024.99   324.7         2024.29
Permanent Ineff=
       F       F
Bank Sta=306.1,322.7
XS Rating Curve= 0 ,0
Exp/Cntr(USF)=0,0
Exp/Cntr=0.3,0.1
LCMann Table=0

Chan Stop Cuts=-1
Use User Specified Reach Order=0
Composite Channel Slope=5